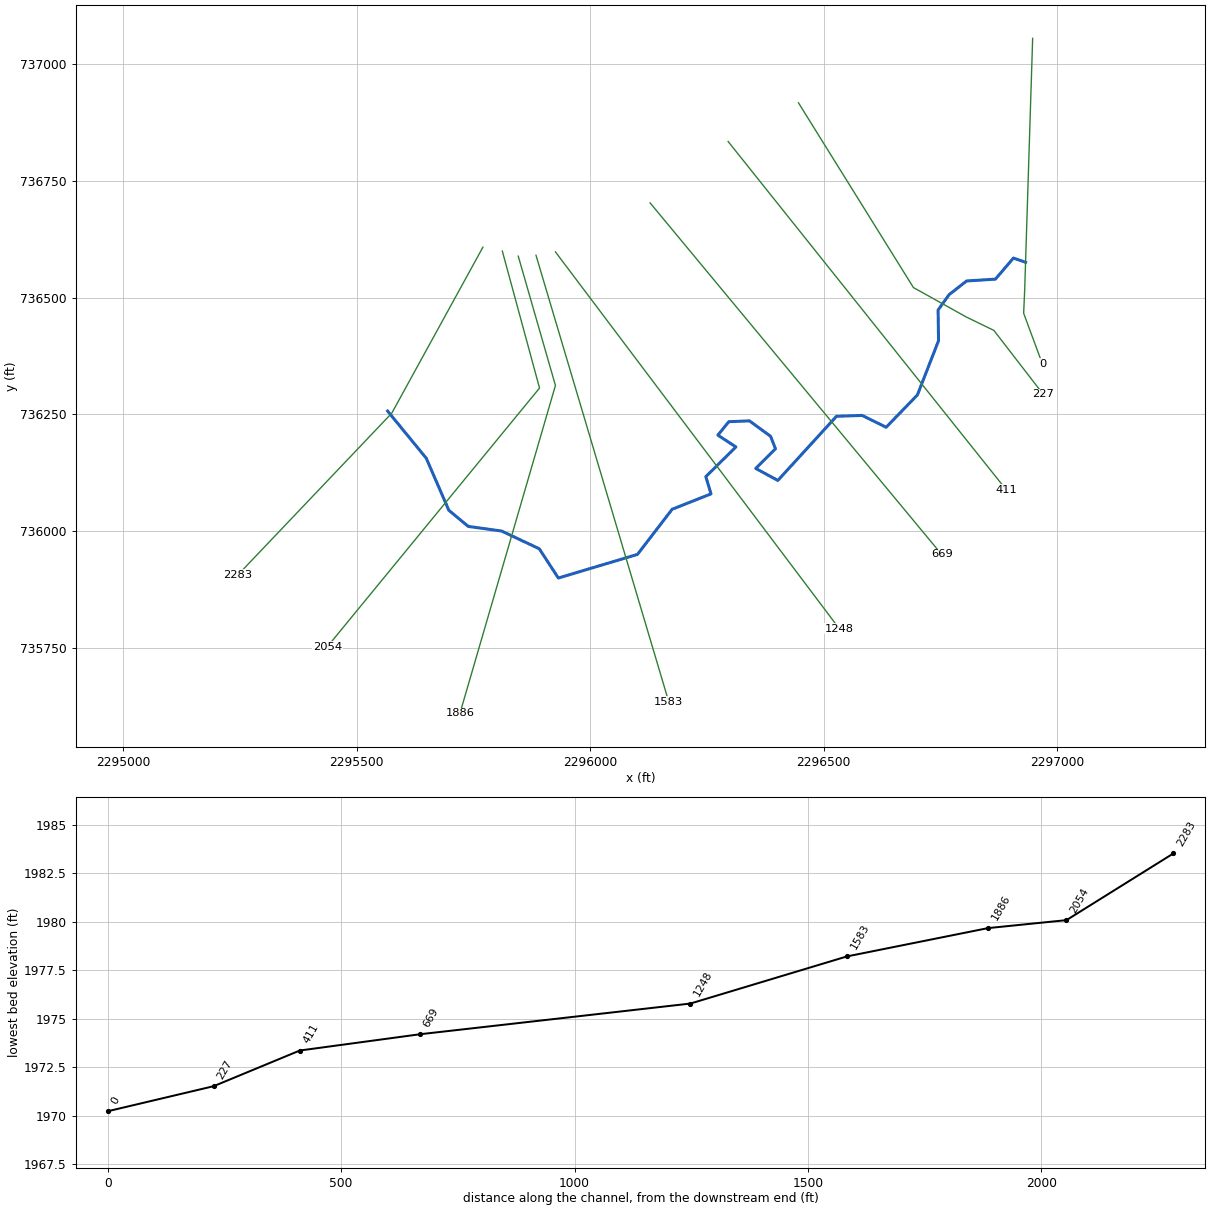
--- DAVISLCKT1.prj (project) ---

Proj Title=DAVISLCKT1
Current Plan=p01
Default Exp/Contr=0,0
English Units
Geom File=g01
Flow File=f01
Plan File=p01
BEGIN DESCRIPTION:
----------MODEL BY WOOD PLC 2022----------
AFH study
Randolph County, WV
HEC-RAS Version: RAS 6.2
Vertical Datum: NAVD88
Projection: NAD 1983 StatePlane West Virginia S FIPS 4702 (US Feet)
Terrain: 1-meter LIDAR (FEMA Region III 3DEP collected 2016-2018)
Land Use: 2019 NLCD
Hydrologic Method:
WV SIR2010-5033 regression equations
Additional Model Notes:
KWSE at downstream boundary with DAVISLK
END DESCRIPTION:
DSS File=dss
DSS Export Rating Curves= 0
DSS Export Rating Curve Sorted= 0
DSS Export Volume Flow Curves= 0
DXF OffsetX= 0
DXF OffsetY= 0
DXF ScaleX= 0
DXF ScaleY= 0

--- DAVISLCKT1.p01 (plan) ---

Plan Title=Floodplain
Program Version=6.20
Short Identifier=Floodplain
Geom File=g01
Flow File=f01
Subcritical Flow
K Sum by GR= 0
Std Step Tol= 0.01
Critical Tol= 0.01
Num of Std Step Trials= 20
Max Error Tol= 0.3
Flow Tol Ratio= 0.001
Split Flow NTrial= 30
Split Flow Tol= 0.02
Split Flow Ratio= 0.02
Log Output Level= 0
Friction Slope Method= 1
Unsteady Friction Slope Method= 2
Unsteady Bridges Friction Slope Method= 1
Parabolic Critical Depth
Global Vel Dist= 0 , 0 , 0
Global Log Level= 0
CheckData=True
Encroach Param=-1 ,0,0, 0
Computation Interval=0.1SEC
Output Interval=1SEC
Instantaneous Interval=Max Profile
Mapping Interval=1HOUR
Computation Time Step Use Courant=        0
Computation Time Step Use Time Series=    0
Computation Time Step Count To Double=0
Computation Time Step Max Doubling=0
Computation Time Step Max Halving=0
Computation Time Step Residence Courant=0
Run HTab= 0
Run UNet= 0
Run Sediment= 0
Run PostProcess= 0
Run WQNet= 0
Run RASMapper= 0
UNET Theta= 0
UNET Theta Warmup= 0
UNET ZTol= 0
UNET ZSATol= 0
UNET MxIter= 0
UNET Max Iter WO Improvement= 0
UNET MaxInSteps= 0
UNET DtIC= 0
UNET DtMin= 0
UNET MaxCRTS= 0
UNET WFStab= 0
UNET SFStab= 0
UNET WFX= 1
UNET SFX= 1
UNET Gravity=32.174
UNET 1D Methodology=Finite Difference
UNET DSS MLevel= 1
UNET Pardiso=0
UNET DZMax Abort= 0
UNET Use Existing IB Tables= 0
UNET Froude Reduction=False
UNET Froude Limit= 0
UNET Froude Power= 0
UNET D1 Cores= 0
UNET WindReference=Eulerian
UNET WindDragFormulation=Hsu (1988)
UNET D2 Coriolis=0
UNET D2 Cores= 0
UNET D2 Theta= 1
UNET D2 Theta Warmup= 1
UNET D2 Z Tol= 0.01
UNET D2 Volume Tol= 0.01
UNET D2 Max Iterations= 20
UNET D2 Equation= 0
UNET D2 RampUpFraction=0.1
UNET D2 TimeSlices= 1
UNET D2 Turbulence Formulation=Non-Conservative (original)
UNET D2 Eddy Viscosity=0.3
UNET D2 Transverse Eddy Viscosity=0.1
UNET D2 Smagorinsky Mixing=0
UNET D2 BCVolumeCheck=0
UNET D2 Cores=0
UNET D2 SolverType=PARDISO (Direct)
UNET D2 Minimum Iterations= 2147483647
UNET D2 Maximum Iterations= 2147483647
UNET D2 Restart Number= 10
UNET D2 Relaxation Coeff=1.3
UNET D2 SOR Precondition Iterations= 10
UNET D2 ILUT Maximum Fill= 8
UNET D2 ILUT Tolerance=1E-08
UNET D1D2 MaxIter= 0
UNET D1D2 ZTol=0.01
UNET D1D2 QTol=0.1
UNET D1D2 MinQTol=1
DSS File=dss
Write IC File= 0
Write IC File at Fixed DateTime=0
Write IC File at Sim End=0
Echo Input=False
Echo Parameters=False
Echo Output=False
Write Detailed= 0
HDF Write Warmup=0
HDF Write Time Slices=0
HDF Flush=0
HDF Compression= 1
HDF Chunk Size= 1
HDF Spatial Parts= 1
HDF Use Max Rows=0
HDF Fixed Rows= 1
Calibration Method= 0
Calibration Iterations= 20
Calibration Max Change=0.05
Calibration Tolerance=0.2
Calibration Maximum=1.5
Calibration Minimum=0.5
Calibration Optimization Method= 1
WQ AD Non Conservative
WQ ULTIMATE=-1
WQ Max Comp Step=1HOUR
WQ Output Interval=15MIN
WQ Output Selected Increments= 0
WQ Output face flow=0
WQ Output face velocity=0
WQ Output face area=0
WQ Output face dispersion=0
WQ Output cell volume=0
WQ Output cell surface area=0
WQ Output cell continuity=0
WQ Output cumulative cell continuity=0
WQ Output face conc=0
WQ Output face dconc_dx=0
WQ Output face courant=0
WQ Output face peclet=0
WQ Output face adv mass=0
WQ Output face disp mass=0
WQ Output cell mass=0
WQ Output cell source sink temp=0
WQ Output nsm pathways=0
WQ Output nsm derived pathways=0
WQ Create Restart=0
WQ Fixed Restart=0
WQ System Summary=0
WQ Write To DSS=0
Sorting and Armoring Iterations= 10
XS Update Threshold= 0.02
Bed Roughness Predictor= 0
Hydraulics Update Threshold= 0.02
Energy Slope Method= 1
Volume Change Method= 1
Sediment Retention Method= 0
Sediment TS Multiplier= 1
Warm Up Method= 0
XS Weighting Method= 0
Number of US Weighted Cross Sections= 1
Number of DS Weighted Cross Sections= 1
Upstream XS Weight=0
Main XS Weight=1
Downstream XS Weight=0
Number of DS XS's Weighted with US Boundary= 1
Upstream Boundary Weight= 1
Weight of XSs Associated with US Boundary= 0
Number of US XS's Weighted with DS Boundary= 1
Downstream Boundary Weight= 0.5
Weight of XSs Associated with DS Boundary= 0.5
Percentile Method= 0
Sediment Output Level= 3
Mass or Volume Output= 0
Output Increment Type= 1
Profile and TS Output Increment= 1
Transport Output Increment 1
XS Output Flag= 0
XS Output Increment= 10
Read HDF5 Sediment Hotstart= 0
Sediment Hotstart Type= 0
Write Gradation File= 0
Read Gradation Hotstart= 0
Write HDF5 File= 1
Write Binary Output= 1
Write DSS Sediment File= 0
DSS Sediment Output Type= 1
SV Curve= 0
Specific Gage Flag= 0
Subcell Erosion Methods= 0
Subcell Deposition Methods= 0
Advection Scheme= 1
Matrix Solver= 0
Implicit Weighting Factor= 1
Maximum Outer Loop Convergence Iterations= 5
Convergence Maximum Absolute= 0.001
Convergence RMSE= 0.0001
Grain Fractions Max Abs Error= 0.001
Max Subgrid Regions= 1
Max Subgrid Length Scale= 3.402823E+38
Initial Layer Thickness= 3.402823E+38
Min Layer Thickness= 3.402823E+38
Max Layer Thickness= 3.402823E+38
Number of Layers= 5

--- DAVISLCKT1.f01 (steady flow) ---

Flow Title=Flow
Program Version=6.20
Number of Profiles= 1
Profile Names=P100yr
River Rch & RM=DAVISLCKT1,Main            ,2283
     373
River Rch & RM=DAVISLCKT1,Main            ,0
     639
Boundary for River Rch & Prof#=DAVISLCKT1,Main            , 1
Up Type= 0
Dn Type= 1
Dn Known WS=1973.51
DSS Import GetInterval= 0
DSS Import GetPeak= 0
DSS Import FillOption= 0

--- DAVISLCKT1.g01 (geometry) ---

Geom Title=Geometry
Program Version=6.20

River Reach=DAVISLCKT1      ,Main
Reach XY= 30
2295566.54000002736256.9140000052295649.35300004736155.873000011
     2295697.671736044.3840000032295739.25100003736009.922000021
2295810.77800003736000.0260000082295891.33400004735962.004999995
2295932.13400002735899.4090000092296101.53499998735950.017000005
2296175.84100001736046.719000012     2296259.001736079.531000003
2296247.88900004 736116.51000002     2296312.299736180.052000016
2296273.64900003736205.366000012     2296297.133736234.151999995
2296341.26600002 736235.924000012296386.71699999736202.741000012
2296396.99600004736176.100999996     2296354.763736134.056000009
2296402.05600002736108.3500000092296527.57700002736245.677000016
     2296582.491736247.6160000122296634.00000001736222.238999993
2296700.86399999736291.3390000162296746.13900003736407.533999994
2296745.19799998736473.368000016      2296768.81736506.180000007
2296806.25000001736535.450000018     2296867.942736539.340000018
     2296906.458736584.4469999972296932.46936871736575.507502213

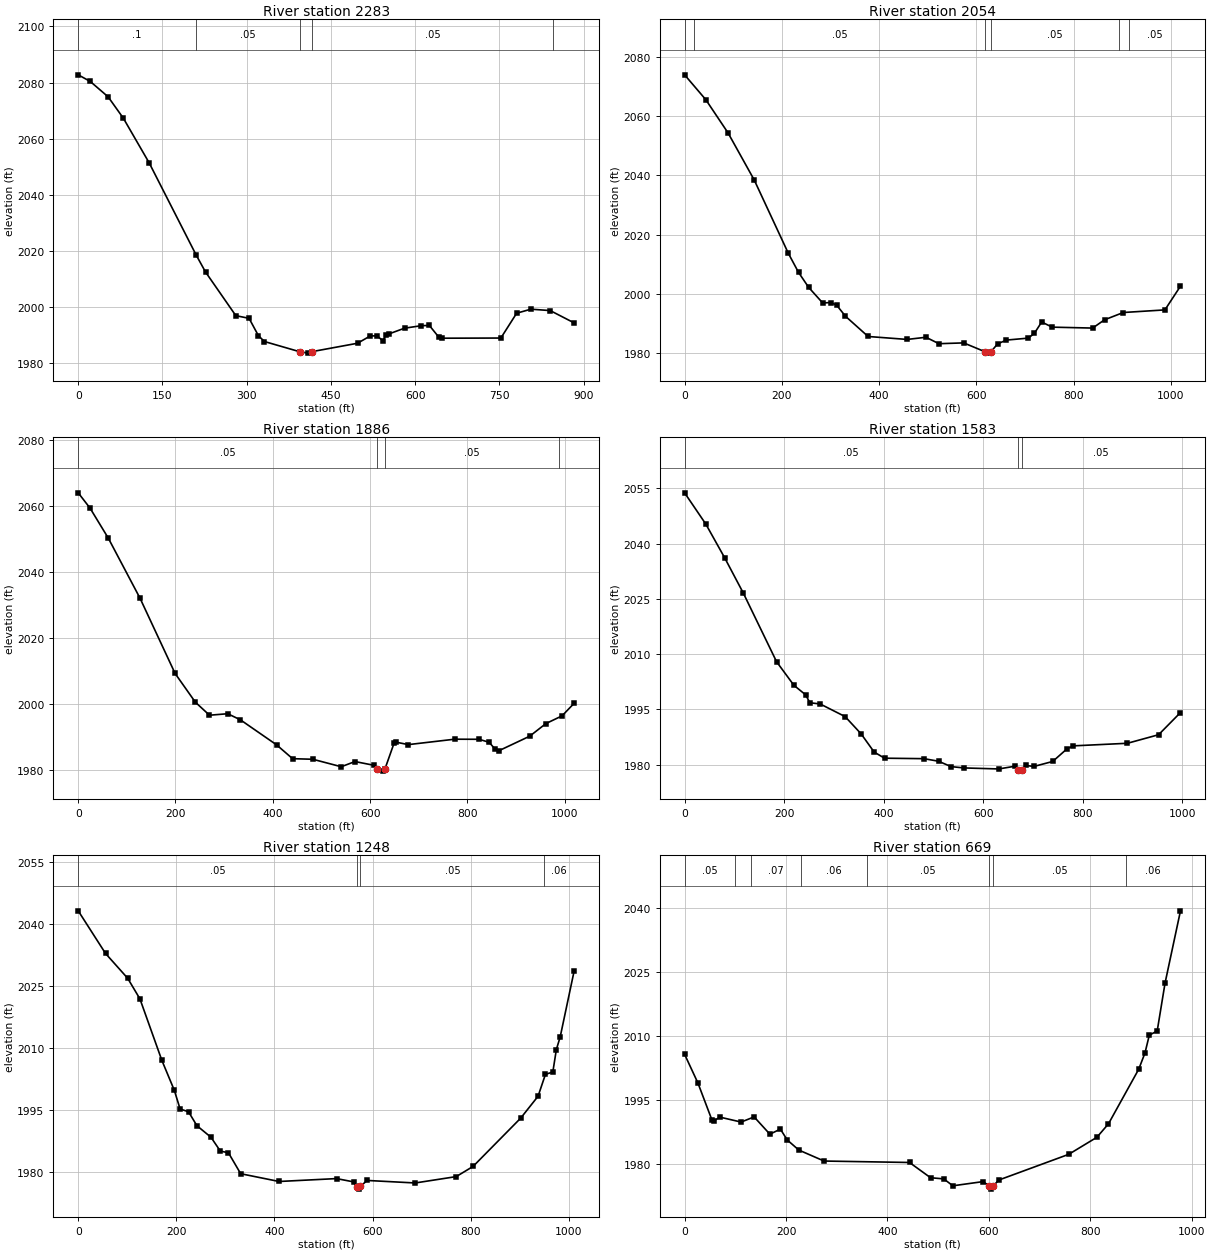
Type RM Length L Ch R = 1 ,2283    ,229.2,229.2,229.2
XS GIS Cut Line= 3
2295770.64996637736607.852105008     2295575.409      736252.295
     2295246.289      735906.391
#Sta/Elev= 30
       0 2082.76    21.3 2080.42    53.2 2074.93    80.4 2067.29   126.3  2051.4
     210 2018.53   226.7 2012.47   280.7 1996.89   304.3 1995.94   320.9 1989.76
   331.6 1987.67395.6521 1983.96   409.9 1983.53415.65211984.035   497.4 1987.05
   520.4 1989.69   532.2 1989.67   542.4 1987.98     548 1989.83   553.5 1990.39
   581.1 1992.42     611 1993.31   625.3 1993.41   641.8 1989.32   647.4 1988.85
   752.7 1988.91   780.8 1997.76   806.2  1999.2   840.6  1998.7   883.1 1994.32
#Mann= 5, -1 ,  0
       0     0.1       0     210    0.05       0395.6521   0.045       0
415.6521    0.05       0  845.64     0.1       0
Bank Sta=395.6521,415.6521
XS Rating Curve= 0 ,0
Exp/Cntr=0.3,0.1

Type RM Length L Ch R = 1 ,2054    ,167.9,167.9,167.9
XS GIS Cut Line= 3
2295812.20643445736599.3299607232295891.82822444736306.177006691
 2295437.6221043735752.443649075
#Sta/Elev= 30
       0 2073.95    43.7 2065.55    89.3 2054.38   143.2 2038.49   213.5 2013.71
   234.3 2007.34   255.1 2002.28   284.1    1997   300.7 1997.16   312.8 1996.26
   330.9 1992.53   377.5  1985.7   457.7 1984.71   496.5 1985.44   523.1 1983.27
   574.1 1983.54   618.6 1980.51   625.4 1980.09   630.1 1980.54   643.8 1983.21
     662 1984.49   706.9 1985.15   719.5 1986.77   734.5 1990.59   756.1 1988.85
   839.3 1988.54   863.8 1991.33   902.4 1993.79     988 1994.67    1020 2002.68
#Mann= 6, -1 ,  0
       0     0.1       0      20    0.05       0   618.6   0.045       0
   630.1    0.05       0  893.77     0.1       0  913.77    0.05       0
Bank Sta=618.6,630.1
XS Rating Curve= 0 ,0
Exp/Cntr(USF)=0,0
Exp/Cntr=0.3,0.1

Type RM Length L Ch R = 1 ,1886    ,302.4,302.4,302.4
XS GIS Cut Line= 3
2295846.26555572736588.610562546 2295925.8873457736311.743883738
2295721.40411234735609.624462971
#Sta/Elev= 30
       0 2063.95    24.4  2059.3    61.8 2050.24   127.2    2032   199.2 2009.25
   240.8 2000.56   269.9 1996.61   307.4 1997.06   333.5 1995.21   407.7 1987.65
   440.7 1983.45   482.4 1983.27   540.7 1981.01     569 1982.58   607.4 1981.46
   614.2 1980.27   627.1 1979.68   630.3 1980.21   649.1 1988.06   653.2 1988.45
   678.7 1987.71     774 1989.35     824 1989.32   844.9 1988.41   857.4 1986.26
   865.7 1985.92   928.2 1990.26   961.5 1994.08   994.7 1996.42  1019.4 2000.21
#Mann= 4, -1 ,  0
       0    0.05       0   614.2   0.045       0   630.3    0.05       0
  988.09     0.1       0
Bank Sta=614.2,630.3
XS Rating Curve= 0 ,0
Exp/Cntr(USF)=0,0
Exp/Cntr=0.3,0.1

Type RM Length L Ch R = 1 ,1583    ,335.4,335.4,335.4
XS GIS Cut Line= 2
2295884.26686457736590.4201486822296168.37188792735634.958668875
#Sta/Elev= 30
       0 2053.76    42.7 2045.26    80.6 2036.11   118.1 2026.53   184.9 2007.91
   219.7 2001.52   243.3 1998.93   251.8 1996.78   272.5 1996.45   322.7 1993.02
   354.8 1988.34     381  1983.4   401.9 1981.73   481.2  1981.6   510.4 1980.91
   535.5 1979.45   561.1 1979.09   631.5 1978.81   664.8 1979.57670.22241978.651
   673.2 1978.22678.22231978.649   685.7 1979.75   702.4  1979.5   739.9 1980.84
   769.1 1984.32   781.7 1985.08   890.2 1985.78   952.8  1988.1   996.8 1994.12
#Mann= 3, -1 ,  0
       0    0.05       0670.2224   0.045       0678.2223    0.05       0
Bank Sta=670.2224,678.2223
XS Rating Curve= 0 ,0
Exp/Cntr(USF)=0,0
Exp/Cntr=0.3,0.1

Type RM Length L Ch R = 1 ,1248    ,578.7,578.7,578.7
XS GIS Cut Line= 2
 2295925.8873457736597.658493226 2296533.9082874735790.583076571
#Sta/Elev= 30
       0 2043.14    55.7 2032.82   100.8 2026.82   125.8 2021.82   170.5 2006.94
   195.9 1999.69   207.6 1995.19   224.8 1994.51   241.9 1991.14   270.5 1988.35
   289.6    1985   306.1 1984.59   331.1 1979.52   409.3 1977.64   526.4 1978.34
   562.2 1977.52568.37951976.344   571.5 1975.79574.95951976.448   588.8 1977.89
   686.7 1977.28   770.3 1978.82   804.6 1981.28   901.7 1992.97   937.1 1998.27
   952.1 2003.56   967.2 2004.14   974.4 2009.58   982.2 2012.63  1010.5 2028.52
#Mann= 4, -1 ,  0
       0    0.05       0568.3795   0.045       0574.9595    0.05       0
     950    0.06       0
Bank Sta=568.3795,574.9595
XS Rating Curve= 0 ,0
Exp/Cntr(USF)=0,0
Exp/Cntr=0.3,0.1

Type RM Length L Ch R = 1 ,669     ,257.9,257.9,257.9
XS GIS Cut Line= 2
2296128.56099294736702.6144891142296752.86820985735949.826656539
#Sta/Elev= 30
       0 2005.79    26.3 1999.06    53.8 1990.44    57.6 1990.16    69.4 1991.08
   111.5 1989.92   137.1 1991.13   168.2 1987.08   188.9 1988.27   202.4 1985.73
   225.3 1983.36   275.1 1980.79   443.6 1980.45   485.1 1976.88   511.1 1976.61
   529.1 1974.99   589.1 1975.98600.38271974.921   604.7 1974.21608.60271974.937
   619.7 1976.34   757.6 1982.36   813.2 1986.36     836 1989.51   895.7 2002.31
     908 2006.11   916.5 2010.27   932.1 2011.26   947.6 2022.49     978  2039.4
#Mann= 8, -1 ,  0
       0    0.05       0     100    0.06       0     130    0.07       0
     230    0.06       0     360    0.05       0600.3827   0.045       0
608.6027    0.05       0     870    0.06       0
Bank Sta=600.3827,608.6027
XS Rating Curve= 0 ,0
Exp/Cntr(USF)=0,0
Exp/Cntr=0.3,0.1

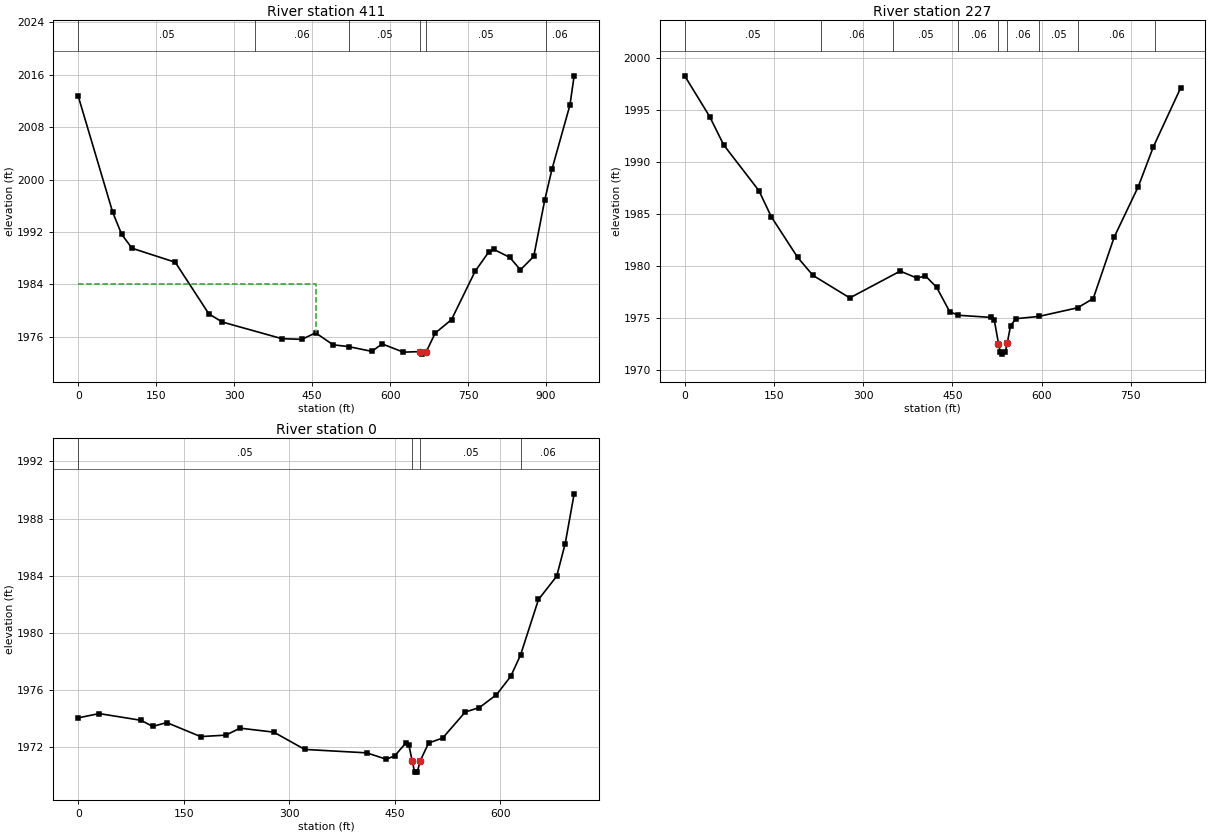
Type RM Length L Ch R = 1 ,411     ,184.7,184.7,184.7
XS GIS Cut Line= 2
 2296295.6682963 736834.002852912296891.02213504736088.453364878
#Sta/Elev= 30
       0 2012.74    66.4    1995    83.5 1991.67   103.4 1989.53   186.7 1987.39
   251.4  1979.5   277.5 1978.26   391.8 1975.73   430.3 1975.62   456.6 1976.62
   490.5 1974.79     520 1974.52   564.9 1973.79   584.6 1974.93   625.6 1973.67
   658.4 1973.76   661.4 1973.37   669.8 1973.77   686.7 1976.57   718.2 1978.64
   763.6 1986.02   789.7 1988.94   799.6 1989.35   830.3 1988.13   850.8 1986.23
   876.4 1988.29   897.5 1996.88   911.7 2001.67   945.9 2011.35   954.1 2015.84
#Mann= 6, -1 ,  0
       0    0.05       0     340    0.06       0     520    0.05       0
   658.4   0.045       0   669.8    0.05       0     900    0.06       0
#XS Ineff= 2 , 0
          457.04 1984.05
Permanent Ineff=
       F       F
Bank Sta=658.4,669.8
XS Rating Curve= 0 ,0
Exp/Cntr(USF)=0,0
Exp/Cntr=0.3,0.1

Type RM Length L Ch R = 1 ,227     ,226.7,226.7,226.7
XS GIS Cut Line= 5
2296446.23252322736916.8508418552296692.35423296736521.388505033
2296805.73727949736458.2055859762296864.59260135736429.643444485
2296970.18597292736292.891373102
#Sta/Elev= 30
       0 1998.31      42 1994.39    65.6 1991.66   124.8 1987.26   145.7 1984.74
   189.9 1980.84   215.6 1979.11   277.6 1976.94   362.4 1979.52   390.7 1978.84
   404.8 1979.06   423.6 1977.96   445.5 1975.62     460 1975.27   515.8 1975.06
   520.5 1974.82   527.6 1972.55   530.5 1971.77   534.3 1971.53   538.9 1971.73
   542.3 1972.59     548 1974.28     557 1974.94   595.6 1975.16   660.6 1975.99
   686.9 1976.88   722.2  1982.8   762.7 1987.66   787.9 1991.47   833.8 1997.14
#Mann= 9, -1 ,  0
       0    0.05       0     230    0.06       0     350    0.05       0
     460    0.06       0   527.6   0.045       0   542.3    0.06       0
   595.6    0.05       0  661.02    0.06       0  791.02    0.05       0
Bank Sta=527.6,542.3
XS Rating Curve= 0 ,0
Exp/Cntr(USF)=0,0
Exp/Cntr=0.3,0.1

Type RM Length L Ch R = 1 ,0       ,387.1,387.1,387.1
XS GIS Cut Line= 4
2296947.66111028737054.9472207442296930.58590594736516.066860767
2296928.37882519 736466.342915582296968.58002121736357.706788242
#Sta/Elev= 30
       0 1974.04    29.8 1974.34    89.2 1973.87   105.8 1973.44   125.8 1973.71
   173.9 1972.73   209.9 1972.83   229.9 1973.32   277.9 1973.04   321.9 1971.83
     410 1971.59     438 1971.14     450 1971.39     466  1972.3     470 1972.11
   474.5 1971.05     478 1970.28   481.8 1970.24  485.761971.001     498 1972.28
     518 1972.63     550 1974.45   570.1 1974.76   594.4 1975.66   614.6 1976.94
   628.6 1978.44   654.1 1982.33     680 1983.96   692.1 1986.25   704.8 1989.73
#Mann= 4, -1 ,  0
       0    0.05       0   474.5   0.045       0  485.76    0.05       0
  628.92    0.06       0
Bank Sta=474.5,485.76
XS Rating Curve= 0 ,0
Exp/Cntr=0.3,0.1
LCMann Table=0

Chan Stop Cuts=-1
Use User Specified Reach Order=0
Composite Channel Slope=5